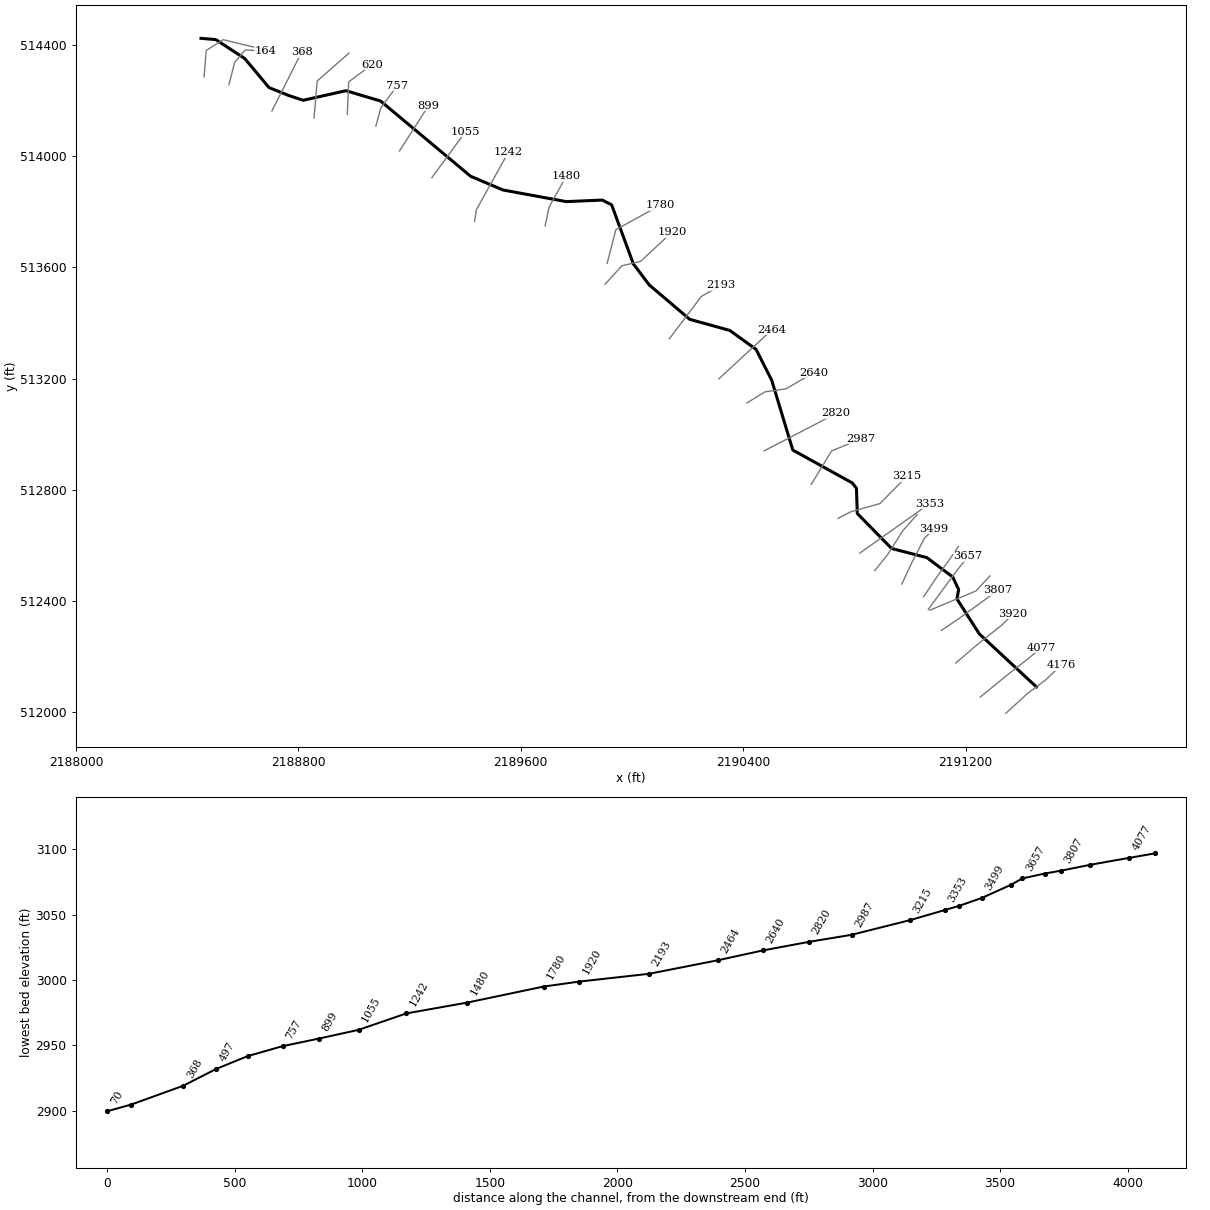
--- MFGAULRV.prj (project) ---

Proj Title=MFGAULRV
Current Plan=p01
Default Exp/Contr=0,0
English Units
Geom File=g01
Flow File=f01
Plan File=p01
BEGIN DESCRIPTION:
----------MODEL BY WOOD PLC 2022----------
AFH study
Randolph County, WV
HEC-RAS Version: RAS 6.2
Vertical Datum: NAVD88
Projection: NAD 1983 StatePlane West Virginia S FIPS 4702 (US Feet)
Terrain: 1-meter LIDAR (FEMA Region III 3DEP collected 2016-2018)
Land Use: 2019 NLCD
Hydrologic Method:
WV SIR2010-5033 regression equations
Additional Model Notes:
Upstream shared XSs with MFGAULYRV from Pocahontas Co.
END DESCRIPTION:
DSS Export Rating Curves= 0
DSS Export Rating Curve Sorted= 0
DSS Export Volume Flow Curves= 0
DXF OffsetX= 0
DXF OffsetY= 0
DXF ScaleX= 0
DXF ScaleY= 0

--- MFGAULRV.p01 (plan) ---

Plan Title=Floodplain
Program Version=6.20
Short Identifier=Floodplain
Geom File=g01
Flow File=f01
Subcritical Flow
K Sum by GR= 0
Std Step Tol= 0.01
Critical Tol= 0.01
Num of Std Step Trials= 20
Max Error Tol= 0.3
Flow Tol Ratio= 0.001
Split Flow NTrial= 30
Split Flow Tol= 0.02
Split Flow Ratio= 0.02
Log Output Level= 0
Friction Slope Method= 1
Unsteady Friction Slope Method= 2
Unsteady Bridges Friction Slope Method= 1
Parabolic Critical Depth
Global Vel Dist= 0 , 0 , 0
Global Log Level= 0
CheckData=False
Encroach Param=-1 ,0,0, 0
Mapping Interval=1HOUR
Computation Time Step Use Courant=        0
Computation Time Step Use Time Series=    0
Computation Time Step Count To Double=0
Computation Time Step Max Doubling=0
Computation Time Step Max Halving=0
Computation Time Step Residence Courant=0
Run HTab= 0
Run UNet= 0
Run Sediment= 0
Run PostProcess= 0
Run WQNet= 0
Run RASMapper=-1
UNET Theta= 0
UNET Theta Warmup= 0
UNET ZTol= 0
UNET ZSATol= 0
UNET MxIter= 0
UNET Max Iter WO Improvement= 0
UNET MaxInSteps= 0
UNET DtIC= 0
UNET DtMin= 0
UNET MaxCRTS= 0
UNET WFStab= 0
UNET SFStab= 0
UNET WFX= 1
UNET SFX= 1
UNET Gravity=32.174
UNET 1D Methodology=Finite Difference
UNET DSS MLevel= 1
UNET Pardiso=0
UNET DZMax Abort= 0
UNET Use Existing IB Tables= 0
UNET Froude Reduction=False
UNET Froude Limit= 0
UNET Froude Power= 0
UNET D1 Cores= 0
UNET WindReference=Eulerian
UNET WindDragFormulation=Hsu (1988)
UNET D2 Coriolis=0
UNET D2 Cores= 0
UNET D2 Theta= 1
UNET D2 Theta Warmup= 1
UNET D2 Z Tol= 0.01
UNET D2 Volume Tol= 0.01
UNET D2 Max Iterations= 20
UNET D2 Equation= 0
UNET D2 RampUpFraction=0.1
UNET D2 TimeSlices= 1
UNET D2 Turbulence Formulation=Non-Conservative (original)
UNET D2 Eddy Viscosity=0.3
UNET D2 Transverse Eddy Viscosity=0.1
UNET D2 Smagorinsky Mixing=0
UNET D2 BCVolumeCheck=0
UNET D2 Cores=0
UNET D2 SolverType=PARDISO (Direct)
UNET D2 Minimum Iterations= 2147483647
UNET D2 Maximum Iterations= 2147483647
UNET D2 Restart Number= 10
UNET D2 Relaxation Coeff=1.3
UNET D2 SOR Precondition Iterations= 10
UNET D2 ILUT Maximum Fill= 8
UNET D2 ILUT Tolerance=1E-08
UNET D1D2 MaxIter= 0
UNET D1D2 ZTol=0.01
UNET D1D2 QTol=0.1
UNET D1D2 MinQTol=1
Write IC File= 0
Write IC File at Fixed DateTime=0
Write IC File at Sim End=0
Echo Input=False
Echo Parameters=False
Echo Output=False
Write Detailed= 0
HDF Write Warmup=0
HDF Write Time Slices=0
HDF Flush=0
HDF Compression= 1
HDF Chunk Size= 1
HDF Spatial Parts= 1
HDF Use Max Rows=0
HDF Fixed Rows= 1
Calibration Method= 0
Calibration Iterations= 20
Calibration Max Change=0.05
Calibration Tolerance=0.2
Calibration Maximum=1.5
Calibration Minimum=0.5
Calibration Optimization Method= 1
WQ AD Non Conservative
WQ ULTIMATE=-1
WQ Max Comp Step=1HOUR
WQ Output Interval=15MIN
WQ Output Selected Increments= 0
WQ Output face flow=0
WQ Output face velocity=0
WQ Output face area=0
WQ Output face dispersion=0
WQ Output cell volume=0
WQ Output cell surface area=0
WQ Output cell continuity=0
WQ Output cumulative cell continuity=0
WQ Output face conc=0
WQ Output face dconc_dx=0
WQ Output face courant=0
WQ Output face peclet=0
WQ Output face adv mass=0
WQ Output face disp mass=0
WQ Output cell mass=0
WQ Output cell source sink temp=0
WQ Output nsm pathways=0
WQ Output nsm derived pathways=0
WQ Create Restart=0
WQ Fixed Restart=0
WQ System Summary=0
WQ Write To DSS=0
Sorting and Armoring Iterations= 10
XS Update Threshold= 0.02
Bed Roughness Predictor= 0
Hydraulics Update Threshold= 0.02
Energy Slope Method= 1
Volume Change Method= 1
Sediment Retention Method= 0
Sediment TS Multiplier= 1
Warm Up Method= 0
XS Weighting Method= 0
Number of US Weighted Cross Sections= 1
Number of DS Weighted Cross Sections= 1
Upstream XS Weight=0
Main XS Weight=1
Downstream XS Weight=0
Number of DS XS's Weighted with US Boundary= 1
Upstream Boundary Weight= 1
Weight of XSs Associated with US Boundary= 0
Number of US XS's Weighted with DS Boundary= 1
Downstream Boundary Weight= 0.5
Weight of XSs Associated with DS Boundary= 0.5
Percentile Method= 0
Sediment Output Level= 3
Mass or Volume Output= 0
Output Increment Type= 1
Profile and TS Output Increment= 1
Transport Output Increment 1
XS Output Flag= 0
XS Output Increment= 10
Read HDF5 Sediment Hotstart= 0
Sediment Hotstart Type= 0
Write Gradation File= 0
Read Gradation Hotstart= 0
Write HDF5 File= 1
Write Binary Output= 1
Write DSS Sediment File= 0
DSS Sediment Output Type= 1
SV Curve= 0
Specific Gage Flag= 0
Subcell Erosion Methods= 0
Subcell Deposition Methods= 0
Advection Scheme= 1
Matrix Solver= 0
Implicit Weighting Factor= 1
Maximum Outer Loop Convergence Iterations= 5
Convergence Maximum Absolute= 0.001
Convergence RMSE= 0.0001
Grain Fractions Max Abs Error= 0.001
Max Subgrid Regions= 1
Max Subgrid Length Scale= 3.402823E+38
Initial Layer Thickness= 3.402823E+38
Min Layer Thickness= 3.402823E+38
Max Layer Thickness= 3.402823E+38
Number of Layers= 5

--- MFGAULRV.f01 (steady flow) ---

Flow Title=Flow
Program Version=6.20
Number of Profiles= 1
Profile Names=P100yr
River Rch & RM=MFGAULRV,Main,4176
     849
Boundary for River Rch & Prof#=MFGAULRV,Main            , 1
Up Type= 0
Dn Type= 3
Dn Slope=0.04702
DSS Import GetInterval= 0
DSS Import GetPeak= 0
DSS Import FillOption= 0

--- MFGAULRV.g01 (geometry) ---

Geom Title=Geometry
Program Version=6.20

River Reach=MFGAULRV        ,Main
Reach XY= 30
2191454.85678507512090.9956309942191249.58400004      512281.603
2191169.03399999512407.4800000042191175.41600002512440.796000004
2191153.89300004512486.3860000222191060.99000001512555.859000027
2190934.02585116512588.879739895     2190810.691512714.629999995
2190807.67587411512805.1229689272190792.61298837512824.578893647
     2190578.744512942.797999993     2190502.868513193.931999996
2190446.64999999513304.8780000212190352.05500001513373.114000008
     2190208.059513412.9760000112190062.39200003513536.709999993
2190005.21200003513612.4430000042189927.10500002513824.902999997
2189893.54400001513842.0160000032189763.90802203513836.454618558
2189536.25470088513878.2793597432189419.92986807513927.625013068
2189095.87099999 514198.314000012188971.33854282514235.408435687
2188817.52723512 514200.955124112188764.65449579514218.466991529
2188694.54400004514246.7610000072188607.69844528514350.821242049
2188503.22115111514419.3068172482188450.09219259514423.785621047

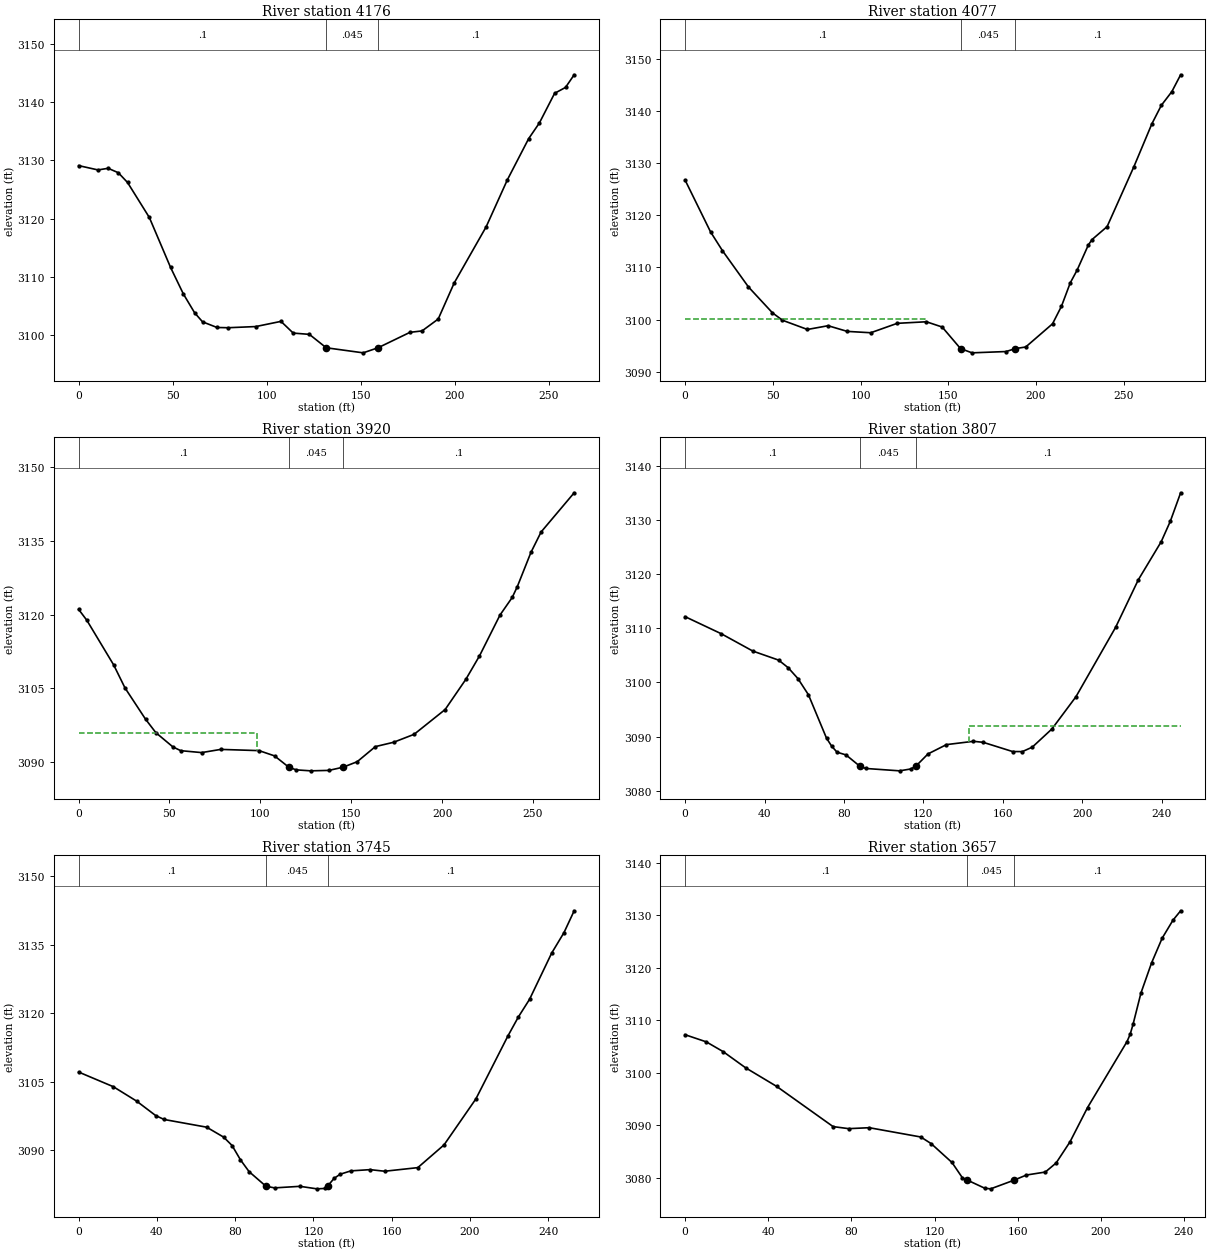
Type RM Length L Ch R = 1 ,4176    ,99.2,99.2,99.2
XS GIS Cut Line= 4
2191344.57454203511995.6522036592191423.30262783512067.330013115
  2191489.105207512116.6819474942191543.15732561512168.383973987
#Sta/Elev= 30
       0 3129.11    10.3 3128.37    15.7 3128.65    21.1 3127.89      26 3126.22
    37.6 3120.21    48.9 3111.63    55.7 3107.08    61.7 3103.84    65.9  3102.3
    73.6 3101.33    79.5 3101.29    94.2 3101.49   107.6 3102.38   114.1 3100.37
   122.7 3100.15  131.66 3097.85   151.3 3096.98   159.2 3097.85   176.2  3100.5
   182.6 3100.74   191.2 3102.78   199.7 3108.97   216.7 3118.61     228 3126.69
   239.3 3133.74     245 3136.43   253.1 3141.52   258.9 3142.53   263.5  3144.7
#Mann= 3 ,-1,0
       0      .1       0  131.66    .045       0   159.2      .1       0
Bank Sta=131.66,159.2
XS Rating Curve= 0 ,0
Exp/Cntr=0.3,0.1

Type RM Length L Ch R = 1 ,4077    ,156.4,156.4,156.4
XS GIS Cut Line= 4
2191252.92094961512054.4045064922191359.85014077512141.357914684
2191430.35290417512196.5850793472191472.65456221512231.836461047
#Sta/Elev= 30
       0 3126.79    14.5 3116.84    21.3 3113.22    36.1 3106.26    49.8 3101.28
    55.5 3099.86    69.7 3098.09    81.5 3098.81    92.4 3097.72   105.8 3097.46
   120.9 3099.27   137.5 3099.57   146.5 3098.56  156.95 3094.42   163.5  3093.6
   182.9 3093.85  188.27 3094.42   194.1 3094.72   209.4 3099.18   214.5 3102.56
   219.5 3107.05   223.4 3109.49   229.8 3114.32   231.9 3115.36   240.5 3117.85
   255.8 3129.39     266 3137.59   271.4 3141.15   277.4 3143.79   282.4 3147.02
#Mann= 3 ,-1,0
       0      .1       0  156.95    .045       0  188.27      .1       0
#XS Ineff= 2 , 0
          136.96 3100.09
Permanent Ineff=
       F       F
Bank Sta=156.95,188.27
XS Rating Curve= 0 ,0
Exp/Cntr=0.3,0.1

Type RM Length L Ch R = 1 ,3920    ,113.4,113.4,113.4
XS GIS Cut Line= 4
2191164.79249536512176.6092963842191238.82039693512240.061783443
2191332.82408146512315.2647310692191371.60060133512354.041250938
#Sta/Elev= 30
       0 3121.07     4.5 3118.86    19.3 3109.74    25.5 3105.07    36.8  3098.7
    42.5 3095.94    51.9 3093.03    56.2 3092.27    67.7 3091.88    78.2 3092.53
    99.3 3092.28   107.8 3091.21  115.66  3088.9   119.7 3088.36   127.7 3088.16
   137.7 3088.25  145.51  3088.9   153.3 3090.02   163.3  3093.1   173.3 3093.98
   184.6  3095.6   201.7 3100.66   213.1 3106.82   220.6 3111.59   231.9 3119.93
   238.6  3123.5   241.4  3125.7   248.9 3132.68   254.5 3136.85   272.7 3144.84
#Mann= 3 ,-1,0
       0      .1       0  115.66    .045       0  145.51      .1       0
#XS Ineff= 2 , 0
           98.02  3095.8
Permanent Ineff=
       F       F
Bank Sta=115.66,145.51
XS Rating Curve= 0 ,0
Exp/Cntr=0.3,0.1

Type RM Length L Ch R = 1 ,3807    ,61.8,61.8,61.8
XS GIS Cut Line= 4
2191113.09046887512294.1139020492191174.19286382512335.240514032
 2191258.7961799512396.3429089782191316.37343667512438.644567018
#Sta/Elev= 30
       0 3112.13    18.2 3108.98    34.1 3105.78    47.1 3104.11    51.9 3102.71
    56.8 3100.71    62.1 3097.72    71.2 3089.71    73.8 3088.23    76.5 3087.12
      81 3086.62   87.89 3084.56    90.9 3084.12     108 3083.68   113.7 3084.03
  116.23 3084.56   122.3  3086.8   131.6 3088.52   145.2 3089.13   150.1 3088.94
   164.9 3087.24   169.8 3087.23   174.8 3088.05   184.7 3091.41   196.8 3097.36
   216.8 3110.19   228.2 3118.94   239.7 3125.95   244.3 3129.73   249.5 3134.99
#Mann= 3 ,-1,0
       0      .1       0   87.89    .045       0  116.23      .1       0
#XS Ineff= 1 ,-1
  142.74249.4612    3092
Permanent Ineff=
       T
Bank Sta=87.89,116.23
XS Rating Curve= 0 ,0
Exp/Cntr=0.3,0.1

Type RM Length L Ch R = 1 ,3745    ,87.6,87.6,87.6
XS GIS Cut Line= 3
2191071.82831558 512366.836868922191237.51656271512435.952537722
2191287.69643184512489.919566787
#Sta/Elev= 30
       0 3107.11    17.7 3103.91    29.6 3100.76    39.4 3097.58    43.7 3096.73
    65.4 3095.05    74.1 3092.87    78.4 3091.04    82.7  3087.9    87.1 3085.32
    95.7 3082.13   100.1 3081.77   113.1 3082.11   121.7 3081.56   126.1 3081.65
   127.4 3082.25   130.5 3083.84   133.6 3084.75   139.1 3085.49   148.9 3085.76
   156.4 3085.41   173.3  3086.2   186.7 3091.17     203 3101.25   219.4 3115.05
   224.7 3119.17   230.4 3123.02   241.7 3133.13     248 3137.62   253.2 3142.39
#Mann= 3 ,-1,0
       0      .1       0    95.7    .045       0   127.4      .1       0
Bank Sta=95.7,127.4
XS Rating Curve= 0 ,0
Exp/Cntr=0.3,0.1

Type RM Length L Ch R = 1 ,3657    ,44.9,44.9,44.9
XS GIS Cut Line= 4
2191066.11993241512369.6863019922191131.65048842512459.116237253
2191174.82356062512516.9373160862191209.51620792512560.110388282
#Sta/Elev= 30
       0 3107.22    10.2 3105.86    18.3    3104    29.1 3100.92    44.1 3097.36
    71.2 3089.71    78.7 3089.32    88.6  3089.5   113.4 3087.73   118.4 3086.46
   128.4 3082.87   133.4 3079.96   135.6 3079.55   144.2 3077.96     147 3077.85
   158.4 3079.52   158.4 3079.53   164.2 3080.48   173.3 3081.05   178.5 3082.78
   185.2 3086.82   193.6 3093.33   212.6 3105.91   214.1 3107.28   215.5 3109.19
   219.3 3115.16   224.4 3120.89   229.5 3125.61   234.7 3129.04   238.4 3130.84
#Mann= 3 ,-1,0
       0      .1       0   135.6    .045       0   158.4      .1       0
Bank Sta=135.6,158.4
XS Rating Curve= 0 ,0
Exp/Cntr=0.3,0.1

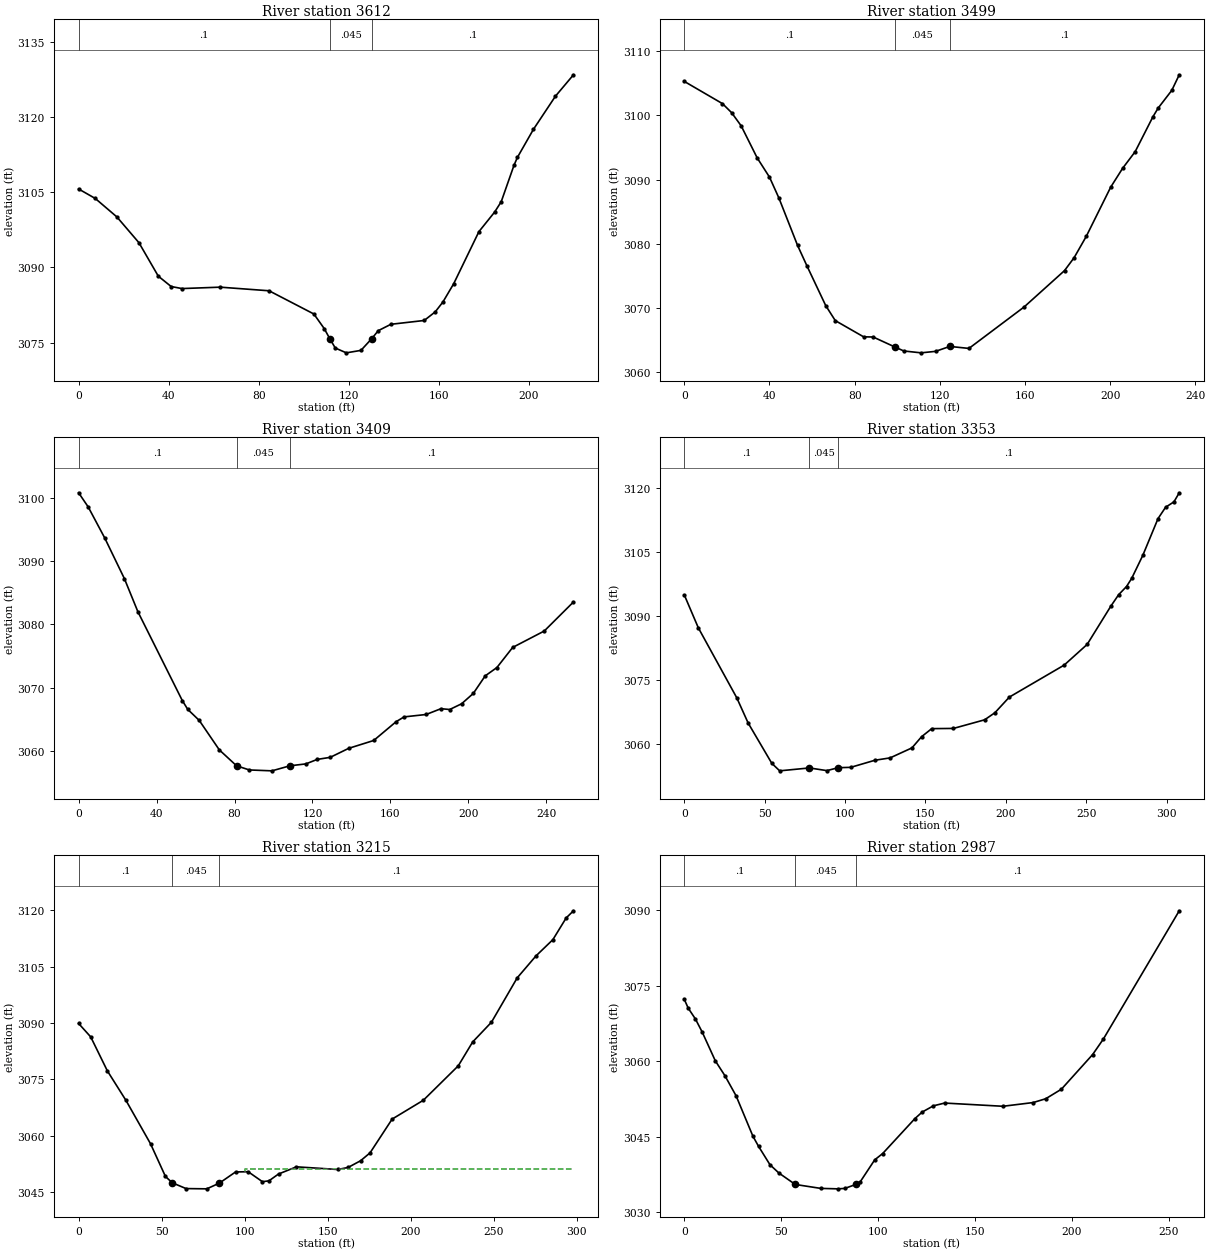
Type RM Length L Ch R = 1 ,3612    ,113.1,113.1,113.1
XS GIS Cut Line= 4
2191049.16245577512415.0736062212191096.27592741512485.315509395
2191140.81957333512546.9913268172191174.22730777512595.818015609
#Sta/Elev= 30
       0 3105.61     7.4 3103.72      17 3100.04    26.8  3094.9    35.4 3088.23
    41.1 3086.17    45.9 3085.76    62.9 3086.04    84.6 3085.32   104.5 3080.69
   109.1 3077.78  111.59 3075.75     114 3073.91   118.9 3072.95   125.4 3073.44
   130.2 3075.78   133.1 3077.37   138.7 3078.64   153.5  3079.4   158.4 3081.12
   161.8 3083.08   166.6 3086.73   177.8 3097.11   184.8 3101.02   187.7 3103.07
   193.4 3110.36   194.9 3111.91     202 3117.49   211.8 3124.11   219.8 3128.37
#Mann= 3 ,-1,0
       0      .1       0  111.59    .045       0   130.2      .1       0
Bank Sta=111.59,130.2
XS Rating Curve= 0 ,0
Exp/Cntr=0.3,0.1

Type RM Length L Ch R = 1 ,3499    ,90,90,90
XS GIS Cut Line= 4
2190970.90989602512460.970442094 2191003.8111856512531.473205493
2191051.98807392512625.4768900262191087.23945562512659.553225669
#Sta/Elev= 30
       0 3105.31    17.9 3101.85    22.2 3100.44    26.7 3098.38    34.2 3093.39
      40 3090.38    44.4 3087.14    53.2 3079.72    57.6 3076.53    66.4 3070.35
    70.9    3068    84.2 3065.47    88.7 3065.44   98.86 3063.89   103.1 3063.26
   111.2 3062.97     118  3063.2   124.7 3063.97   133.7 3063.66   159.6 3070.12
   178.6  3075.8   183.1 3077.81   188.8 3081.13   200.3 3088.82   205.9 3091.76
   211.8 3094.36   220.1 3099.78   222.6 3101.16     229 3103.92   232.5 3106.35
#Mann= 3 ,-1,0
       0      .1       0   98.86    .045       0   124.7      .1       0
Bank Sta=98.86,124.7
XS Rating Curve= 0 ,0
Exp/Cntr=0.3,0.1

Type RM Length L Ch R = 1 ,3409    ,56.6,56.6,56.6
XS GIS Cut Line= 4
2190873.38107331512509.1473304172190919.20786952512565.549541136
2190974.43503419512652.5029493292191026.13706068512711.255252161
#Sta/Elev= 30
       0 3100.87     4.9 3098.64    13.4 3093.71    23.5 3087.26    30.4 3082.03
    53.2 3067.94      56 3066.54    61.9 3064.79    72.2 3060.12   81.04  3057.6
    87.6 3056.94    99.2  3056.8  108.42  3057.6   116.6  3057.9   122.4 3058.61
   129.1 3058.94   138.6 3060.37   151.4 3061.61   162.9 3064.59     167 3065.35
   178.3 3065.73   185.9 3066.65   190.4 3066.52   196.5 3067.43   202.5 3069.07
   208.6 3071.85   214.6 3073.17   222.7 3076.36   238.9 3078.96   253.9 3083.57
#Mann= 3 ,-1,0
       0      .1       0   81.04    .045       0  108.42      .1       0
Bank Sta=81.04,108.42
XS Rating Curve= 0 ,0
Exp/Cntr=0.3,0.1

Type RM Length L Ch R = 1 ,3353    ,137.2,137.2,137.2
XS GIS Cut Line= 2
2190819.81174082 512572.125908262191070.91964802512750.340695985
#Sta/Elev= 30
       0 3094.87     8.7 3087.17    32.6 3070.75    39.7 3064.81    54.4 3055.36
    59.3 3053.59    77.8 3054.27    88.7 3053.64    95.7 3054.33   103.5 3054.41
   118.6 3056.08     128 3056.63   141.6 3058.98   147.6 3061.61   153.9  3063.5
   167.4 3063.55   186.8 3065.57   193.2 3067.23   202.2 3070.91   236.3 3078.42
   250.6 3083.28   265.3 3092.24   270.2 3094.96   275.1 3096.88   278.3 3098.78
   285.2 3104.17   294.7 3112.83   299.4 3115.49   304.6 3116.76   307.9 3118.89
#Mann= 3 ,-1,0
       0      .1       0    77.8    .045       0    95.7      .1       0
Bank Sta=77.8,95.7
XS Rating Curve= 0 ,0
Exp/Cntr(USF)=0,0
Exp/Cntr=0.3,0.1

Type RM Length L Ch R = 1 ,3215    ,228.3,228.3,228.3
XS GIS Cut Line= 4
   2190741.65804512697.2540457282190787.67209941512720.918419139
2190892.07779644 512750.33048102 2190988.9363542512848.353503432
#Sta/Elev= 30
       0 3089.84     7.3 3086.26    17.3 3077.23    28.5 3069.37    43.3 3057.82
    52.3  3049.1    56.4 3047.42    64.7 3045.88    77.2 3045.81    84.8 3047.34
    94.5  3050.3   102.1 3050.37   110.7 3047.71   114.6 3047.94   120.4 3049.76
   131.2 3051.67   156.1 3050.96   162.3 3051.51   169.8 3053.29   175.5 3055.39
   188.8 3064.38   207.6  3069.4   228.6 3078.55   237.3 3084.92   248.6 3090.17
   264.1 3101.98   275.4 3107.82   285.6 3112.16   293.6 3117.94     298 3119.84
#Mann= 3 ,-1,0
       0      .1       0    56.4    .045       0    84.8      .1       0
#XS Ineff= 2 , 0
                             100            3051
Permanent Ineff=
       F       F
Bank Sta=56.4,84.8
XS Rating Curve= 0 ,0
Exp/Cntr(USF)=0,0
Exp/Cntr=0.3,0.1

Type RM Length L Ch R = 1 ,2987    ,166.9,166.9,166.9
XS GIS Cut Line= 3
2190645.22383026512819.4647078242190718.18806497512939.791691396
2190824.43423132512983.314217368
#Sta/Elev= 30
       0 3072.29       2 3070.56     5.7 3068.42     9.2 3065.82      16 3060.08
    20.9 3057.16    26.7 3053.14    35.4  3045.1    38.3 3043.09    44.2 3039.43
    48.8 3037.78   57.273035.501    70.4 3034.72    79.1 3034.63    82.8 3034.71
   88.52  3035.5    90.9 3036.08    98.3  3040.4   102.4 3041.65     119 3048.58
   122.8  3049.9   128.6 3051.14   134.4 3051.69   164.5 3051.05   180.1 3051.79
   186.6 3052.55   194.7 3054.45   210.8 3061.33   216.4 3064.45255.5358 3089.93
#Mann= 3 ,-1,0
       0      .1       0   57.27    .045       0   88.52      .1       0
Bank Sta=57.27,88.52
XS Rating Curve= 0 ,0
Exp/Cntr(USF)=0,0
Exp/Cntr=0.3,0.1

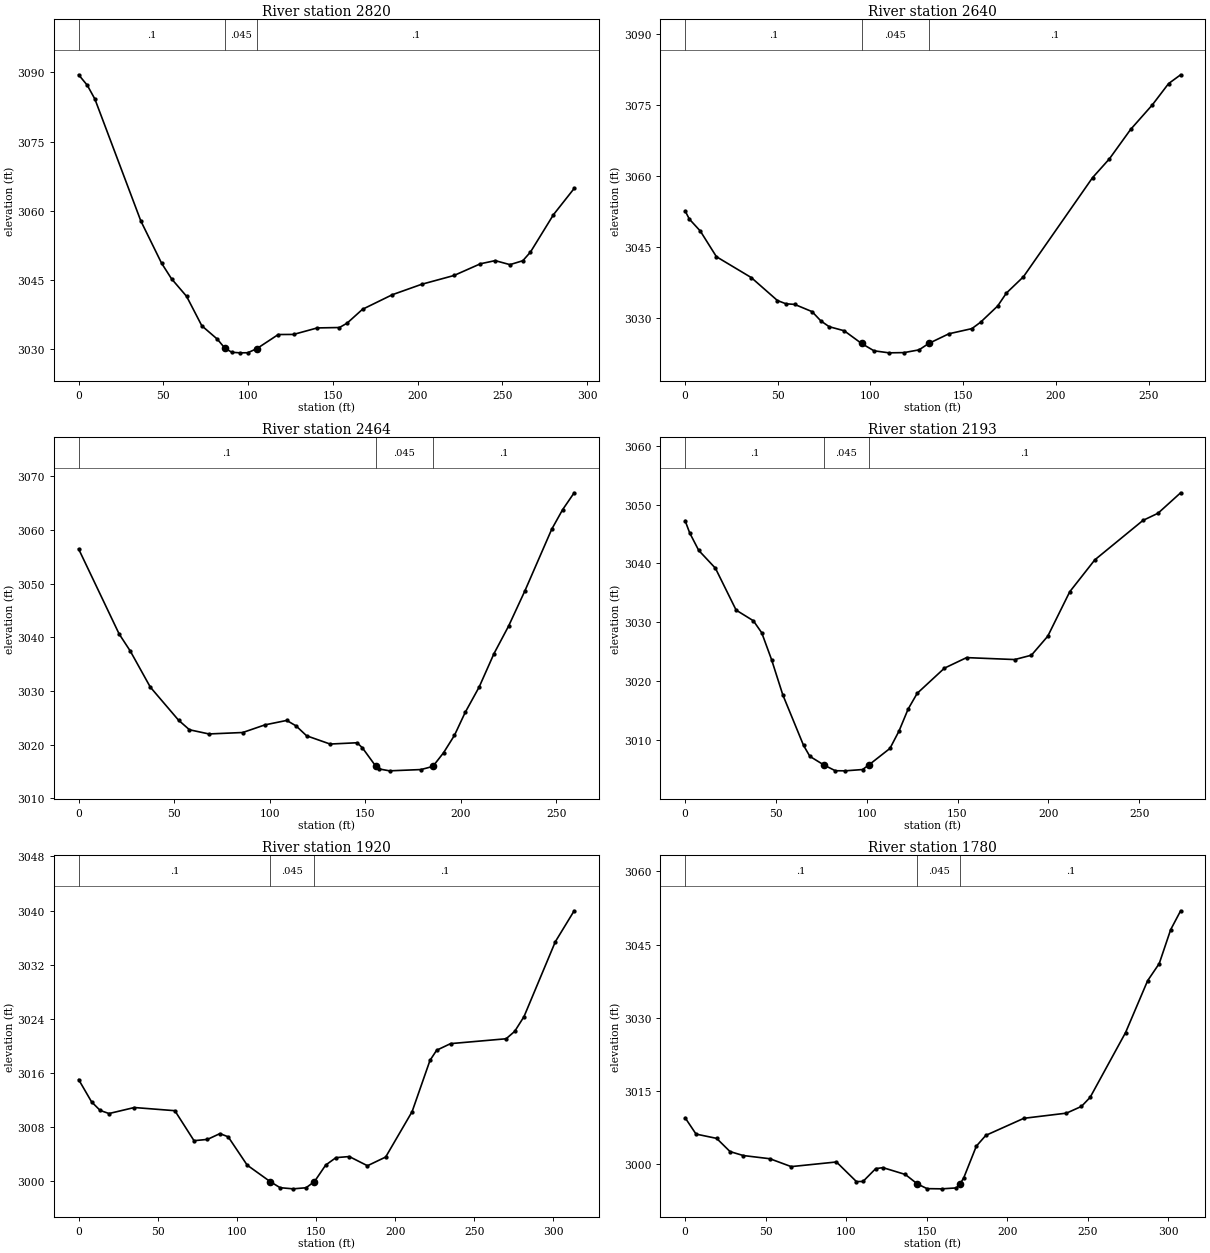
Type RM Length L Ch R = 1 ,2820    ,180.6,180.6,180.6
XS GIS Cut Line= 2
2190475.63553646512939.7905674792190735.07349283513074.682154435
#Sta/Elev= 30
       0  3089.5     5.1 3087.23     9.6 3084.23    36.7 3057.81    48.9 3048.68
    54.8 3045.28    63.7 3041.47    72.7 3035.08    81.8  3032.2    86.3 3030.23
    90.4 3029.34    95.3 3029.22    99.8 3029.24   105.2 3030.14   117.8 3033.19
   126.8 3033.21   140.8 3034.62   153.9 3034.71   158.4 3035.65   167.5 3038.66
   185.1 3041.82   202.4 3044.08   221.5 3045.99   237.1 3048.53   245.8 3049.21
   254.5 3048.34   262.1 3049.19   266.6 3051.06   280.2 3059.18   292.4 3064.86
#Mann= 3 ,-1,0
       0      .1       0    86.3    .045       0   105.2      .1       0
Bank Sta=86.3,105.2
XS Rating Curve= 0 ,0
Exp/Cntr(USF)=0,0
Exp/Cntr=0.3,0.1

Type RM Length L Ch R = 1 ,2640    ,176.1,176.1,176.1
XS GIS Cut Line= 4
2190413.73339719513112.4106417622190478.98410686513152.340180514
2190554.46067401513163.0529835942190653.31062971513220.999509344
#Sta/Elev= 30
       0 3052.67     2.3 3050.93     8.2 3048.41    16.9 3042.98    35.7 3038.57
    49.8 3033.72    54.4 3033.03    59.1  3032.9    68.5 3031.37    73.2 3029.42
    77.7 3028.19    85.8 3027.33   95.19 3024.64   101.9 3023.09     110 3022.66
   118.1 3022.71   126.2 3023.29   131.4 3024.64   142.3 3026.69   154.7 3027.78
   159.4 3029.14   168.6 3032.56   173.3 3035.29   182.5 3038.74   219.8  3059.7
   228.9 3063.68   240.3 3069.88     252 3075.06   260.8 3079.58   267.3 3081.44
#Mann= 3 ,-1,0
       0      .1       0   95.19    .045       0   131.4      .1       0
Bank Sta=95.19,131.4
XS Rating Curve= 0 ,0
Exp/Cntr(USF)=0,0
Exp/Cntr=0.3,0.1

Type RM Length L Ch R = 1 ,2464    ,270.4,270.4,270.4
XS GIS Cut Line= 2
2190312.61741922513198.8368373082190502.99576125513374.944506854
#Sta/Elev= 30
       0 3056.47    21.2 3040.64      27 3037.48    37.5 3030.75    52.3 3024.58
      58  3022.8    68.2 3022.02    85.9 3022.29    97.5 3023.71   108.9 3024.54
   113.8 3023.52   119.3 3021.68   131.6 3020.14   145.7 3020.38   148.5 3019.44
  155.593015.975     157 3015.52   162.7 3015.15   179.2 3015.39  185.393015.975
     191 3018.53   196.7 3021.77   202.3 3026.03   209.6 3030.75   217.4    3037
     225  3042.1   233.5 3048.63   247.6 3060.16   253.3  3063.8259.3411 3066.94
#Mann= 3 ,-1,0
       0      .1       0  155.59    .045       0  185.39      .1       0
Bank Sta=155.59,185.39
XS Rating Curve= 0 ,0
Exp/Cntr(USF)=0,0
Exp/Cntr=0.3,0.1

Type RM Length L Ch R = 1 ,2193    ,273.5,273.5,273.5
XS GIS Cut Line= 3
2190134.75017918 513343.212194812190249.71883927513495.406609379
2190321.54523017513535.231142949
#Sta/Elev= 30
       0 3047.27     2.5  3045.2     7.5 3042.21    16.7 3039.18    28.1 3032.06
    37.6 3030.25    42.2 3028.21    47.6 3023.66    53.8 3017.66    65.2 3009.09
    68.7 3007.21   76.583005.717    82.7 3004.77    88.1 3004.75    97.7 3004.97
  101.043005.716   112.8 3008.56   117.8 3011.52   122.8 3015.24   127.8 3017.92
   142.8  3022.2     155 3023.99   181.5 3023.66   190.7  3024.4   199.7 3027.63
   211.8 3035.18   225.6  3040.6   252.1  3047.3   260.4 3048.52272.8659    3052
#Mann= 3 ,-1,0
       0      .1       0   76.58    .045       0  101.04      .1       0
Bank Sta=76.58,101.04
XS Rating Curve= 0 ,0
Exp/Cntr(USF)=0,0
Exp/Cntr=0.3,0.1

Type RM Length L Ch R = 1 ,1920    ,139.2,139.2,139.2
XS GIS Cut Line= 4
2189903.28298893513539.0990006042189963.79566784 513605.68652903
2190030.99415989513621.2687880552190143.64888068513726.464760338
#Sta/Elev= 30
       0 3014.97     8.2 3011.66    13.6  3010.4    19.2 3009.94    35.2 3010.83
    60.8 3010.36    72.9 3005.92    81.4 3006.11    89.3 3006.97    94.5 3006.49
   106.5  3002.3  121.04 2999.86   127.3 2998.96   135.5 2998.79   143.7 2998.95
  149.02 2999.87   156.1 3002.31   162.6 3003.41     171 3003.57   182.5 3002.21
     194  3003.5   210.7 3010.22     222 3017.81   226.2 3019.31     235 3020.29
   270.1 3021.01   275.5  3022.1   281.4 3024.29   301.2 3035.38   313.1 3039.96
#Mann= 3 ,-1,0
       0      .1       0  121.04    .045       0  149.02      .1       0
Bank Sta=121.04,149.02
XS Rating Curve= 0 ,0
Exp/Cntr(USF)=0,0
Exp/Cntr=0.3,0.1

Type RM Length L Ch R = 1 ,1780    ,300.1,300.1,300.1
XS GIS Cut Line= 3
2189910.84077487513614.1902962932189942.25262995513735.420244228
2190102.07839963513823.605780194
#Sta/Elev= 30
       0 3009.55     6.8  3006.2    19.6 3005.32    27.9 3002.62    36.1 3001.81
    52.7 3001.15    65.9 2999.54      94 3000.49   106.4 2996.48   110.5  2996.5
   118.4 2999.13   122.9 2999.33   136.8 2997.93  144.28 2995.99   150.3 2995.03
   159.4 2994.99   168.5 2995.18  170.83 2996.02   173.1 2997.26   180.9 3003.73
   186.8 3005.94   210.4 3009.43   236.9 3010.49   246.2 3011.87   251.6 3013.73
   273.6 3026.99   287.3 3037.61   294.5 3041.11   301.6 3048.05   307.8 3051.92
#Mann= 3 ,-1,0
       0      .1       0  144.28    .045       0  170.83      .1       0
Bank Sta=144.28,170.83
XS Rating Curve= 0 ,0
Exp/Cntr(USF)=0,0
Exp/Cntr=0.3,0.1

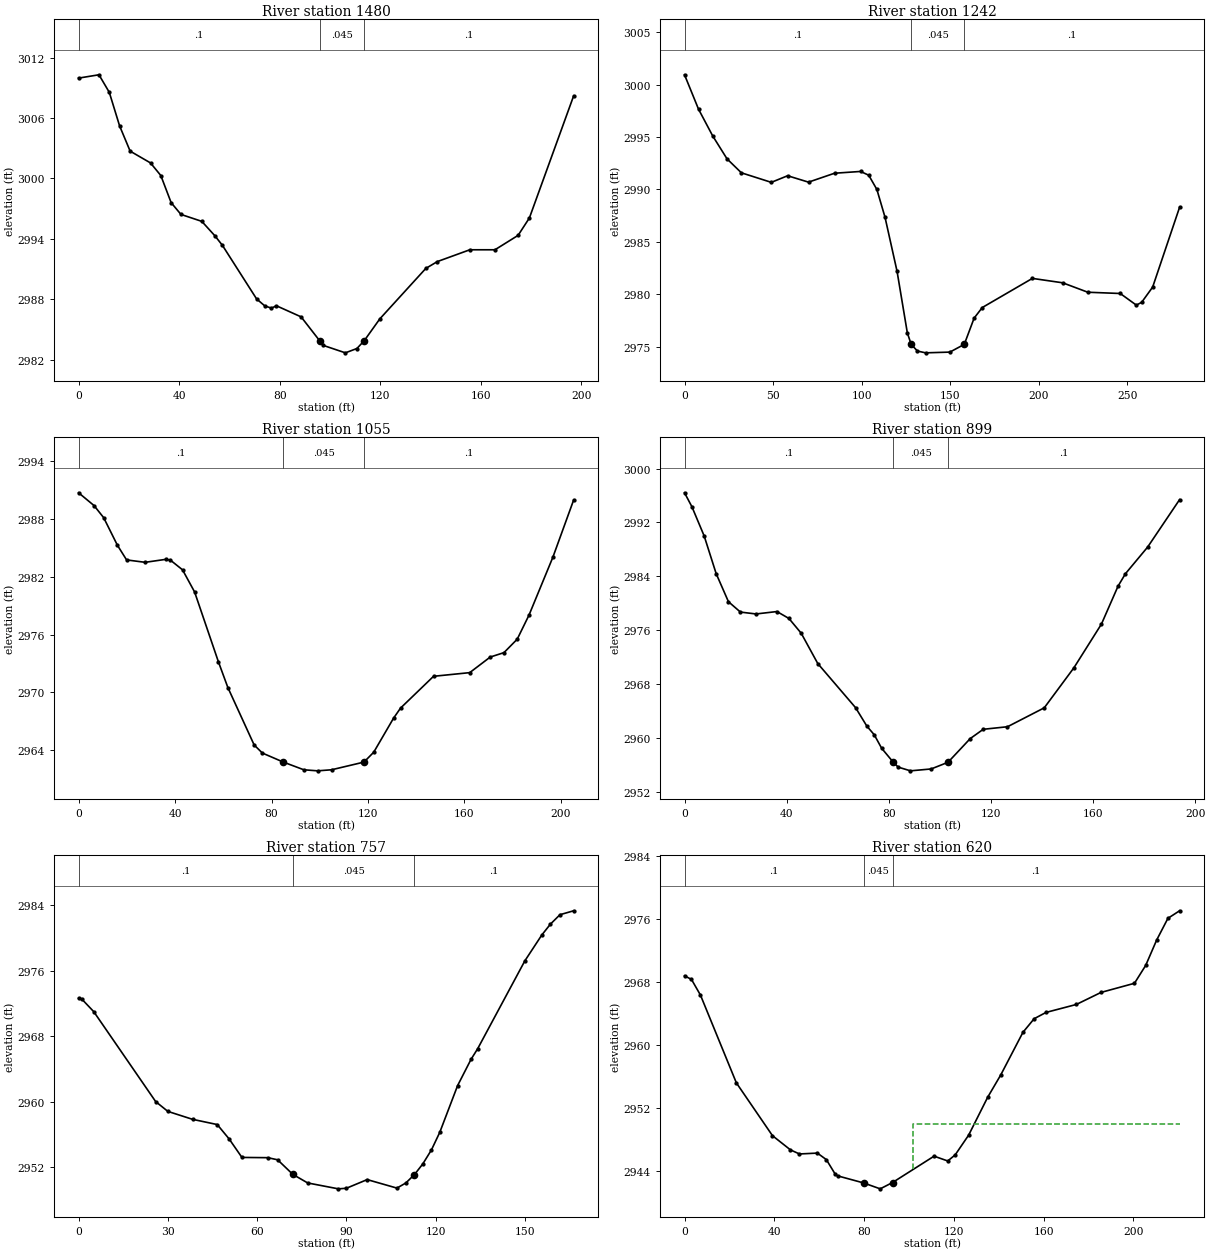
Type RM Length L Ch R = 1 ,1480    ,237.9,237.9,237.9
XS GIS Cut Line= 3
2189687.69677786513749.2447074112189702.30588357 513817.02091706
2189764.26332831513928.565792229
#Sta/Elev= 30
       0 3009.96     8.1 3010.29    12.2 3008.55    16.3 3005.22    20.5 3002.71
    28.6 3001.54    32.7 3000.29    36.8  2997.6    40.7 2996.43      49 2995.74
    54.2 2994.31    57.2 2993.36    70.8 2988.04    74.1 2987.34    76.7 2987.13
    78.7 2987.36    88.5 2986.26   95.82 2983.91    97.3 2983.43   106.1 2982.69
   110.7 2983.12  113.65 2983.91   119.8 2986.06   138.1 2991.07   142.7 2991.75
   155.6 2992.92   165.6 2992.92   174.8 2994.35   179.3 2996.08   196.9  3008.2
#Mann= 3 ,-1,0
       0      .1       0   95.82    .045       0  113.65      .1       0
Bank Sta=95.82,113.65
XS Rating Curve= 0 ,0
Exp/Cntr(USF)=0,0
Exp/Cntr=0.3,0.1

Type RM Length L Ch R = 1 ,1242    ,187.4,187.4,187.4
XS GIS Cut Line= 3
2189434.24179756513765.4126982082189440.64216903513807.655149887
2189555.94734346514014.467515074
#Sta/Elev= 30
       0 3000.94     7.9 2997.66    15.9 2995.11      24 2992.92    32.1 2991.59
      49 2990.68    58.2 2991.31      70  2990.7    84.7 2991.55    99.4 2991.72
     104 2991.36   108.6    2990   113.2 2987.35     120 2982.19   125.8 2976.32
  127.962975.233   131.5 2974.59   136.1 2974.42   149.8 2974.49157.94992975.229
   163.5 2977.73   168.1 2978.74   196.4 2981.52   213.5  2981.1   227.7  2980.2
     246 2980.08   255.1 2978.97   258.1 2979.24   264.3 2980.69   279.5  2988.3
#Mann= 3 ,-1,0
       0      .1       0  127.96    .045       0157.9499      .1       0
Bank Sta=127.96,157.9499
XS Rating Curve= 0 ,0
Exp/Cntr(USF)=0,0
Exp/Cntr=0.3,0.1

Type RM Length L Ch R = 1 ,1055    ,156.4,156.4,156.4
XS GIS Cut Line= 2
2189280.40971207513922.3896275522189401.63117959514088.136985952
#Sta/Elev= 30
       0 2990.74     6.4 2989.41    10.4 2988.15    16.1 2985.28    19.9 2983.76
    27.6 2983.51    36.2 2983.82    38.1 2983.73    43.1 2982.73    48.1 2980.43
      58 2973.15    61.9 2970.49    72.8 2964.52    76.2 2963.68    84.8 2962.75
    93.4 2961.94    99.1 2961.83   104.9 2961.94  118.35 2962.74   122.4 2963.77
   130.6  2967.3   133.5 2968.35   147.2 2971.66   162.2 2972.04   170.7 2973.66
   176.4 2974.12   181.9 2975.52   186.8 2978.03   196.7 2984.05   205.3 2989.99
#Mann= 3 ,-1,0
       0      .1       0    84.8    .045       0  118.35      .1       0
Bank Sta=84.8,118.35
XS Rating Curve= 0 ,0
Exp/Cntr(USF)=0,0
Exp/Cntr=0.3,0.1

Type RM Length L Ch R = 1 ,899     ,141.3,141.3,141.3
XS GIS Cut Line= 2
 2189163.9961232514018.721601545 2189268.6969904514181.947904219
#Sta/Elev= 30
       0  2996.4     2.9 2994.32     7.7 2989.98    12.4 2984.38    17.2 2980.22
    21.9 2978.68      28  2978.4    36.2 2978.76    40.9 2977.73    45.7 2975.54
    52.2 2971.03      67 2964.48    71.4 2961.75    74.3 2960.46    77.2 2958.46
    81.8 2956.36    83.7 2955.65    88.5  2955.1    96.6 2955.38   103.2 2956.37
   111.9 2959.89     117 2961.27   126.5 2961.65   140.9 2964.46   152.5  2970.4
   163.3  2976.9   169.8 2982.53   172.7 2984.38   181.4 2988.34   193.9 2995.38
#Mann= 3 ,-1,0
       0      .1       0    81.8    .045       0   103.2      .1       0
Bank Sta=81.8,103.2
XS Rating Curve= 0 ,0
Exp/Cntr(USF)=0,0
Exp/Cntr=0.3,0.1

Type RM Length L Ch R = 1 ,757     ,137.3,137.3,137.3
XS GIS Cut Line= 3
2189079.01552256514108.2143825942189097.03250956514174.438983452
 2189155.4659809514252.837224172
#Sta/Elev= 30
       0 2972.65       1 2972.56     5.1 2970.99    25.9    2960      30  2958.8
    38.3 2957.83    46.6 2957.19    50.6 2955.43    54.9 2953.17    63.6 2953.14
    66.9 2952.88      72  2951.1      77 2950.05    87.3 2949.33      90  2949.4
      97 2950.46     107 2949.42     110 2950.05   112.9 2951.08   115.7 2952.38
   118.6 2954.09   121.4 2956.24   127.4 2961.96   131.9 2965.16   134.1 2966.44
     150 2977.21   155.7 2980.37   158.6  2981.7   161.8 2982.85   166.4 2983.33
#Mann= 3 ,-1,0
       0      .1       0      72    .045       0   112.9      .1       0
Bank Sta=72,112.9
XS Rating Curve= 0 ,0
Exp/Cntr(USF)=0,0
Exp/Cntr=0.3,0.1

Type RM Length L Ch R = 1 ,620     ,123.3,123.3,123.3
XS GIS Cut Line= 3
 2188976.3008755514150.0499395792188981.15890794514267.252582958
2189064.35088929514328.423157475
#Sta/Elev= 30
       0 2968.77     3.1 2968.31     7.1 2966.32    23.1 2955.17    39.2 2948.46
    47.2 2946.66    51.2 2946.14    59.2 2946.25    63.2 2945.42    67.2 2943.55
    68.2 2943.36    79.8 2942.46    87.2 2941.71   92.68 2942.51   111.2 2945.86
   117.3 2945.25   120.6 2946.02   126.6 2948.53   135.1 2953.35   140.9 2956.17
   150.8 2961.59   155.8 2963.32   161.1 2964.12   174.6 2965.13   185.6 2966.66
   200.5 2967.82   205.5 2970.09   210.4 2973.32   215.4 2976.07   220.6 2977.03
#Mann= 3 ,-1,0
       0      .1       0    79.8    .045       0   92.68      .1       0
#XS Ineff= 2 , 0
                             102            2950
Permanent Ineff=
       F       F
Bank Sta=79.8,92.68
XS Rating Curve= 0 ,0
Exp/Cntr(USF)=0,0
Exp/Cntr=0.3,0.1

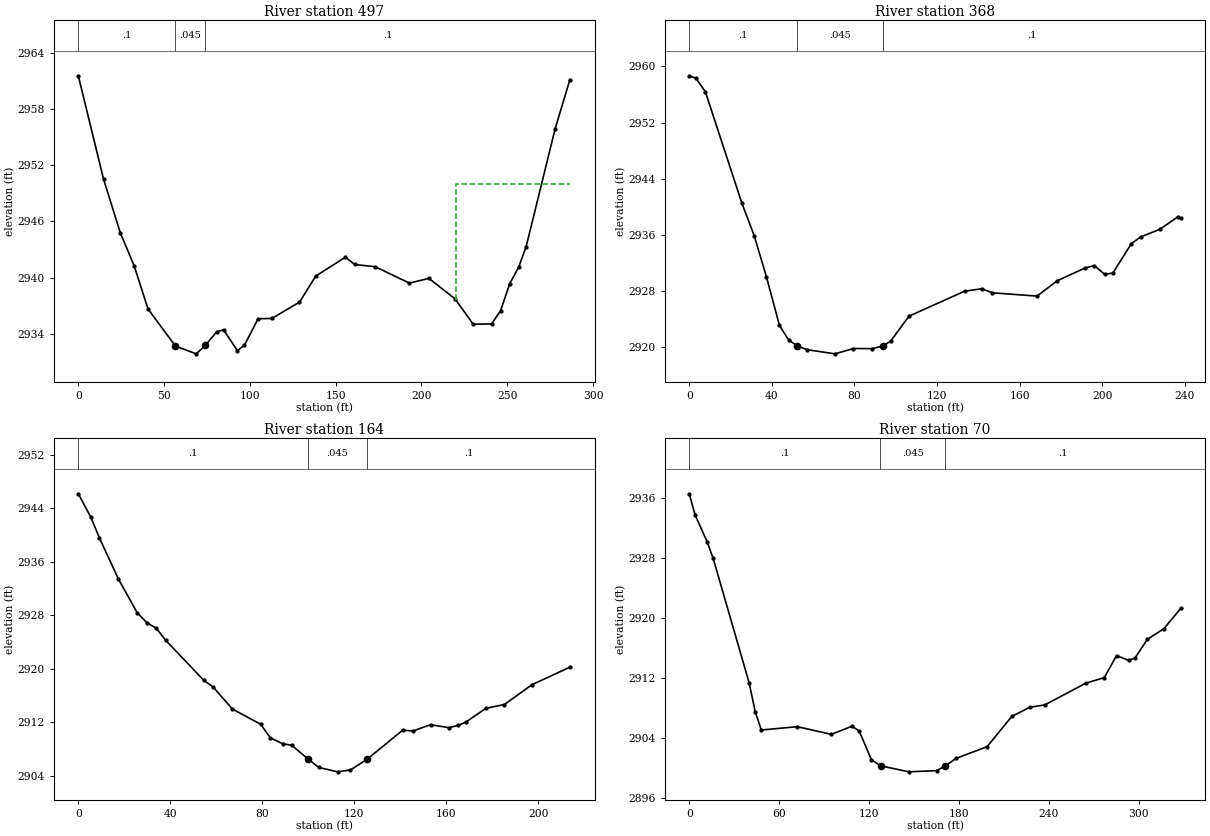
Type RM Length L Ch R = 1 ,497     ,129.2,129.2,129.2
XS GIS Cut Line= 3
2188856.66786099514136.7554913022188867.88213899514270.288871662
2188982.55279491 514370.82092831
#Sta/Elev= 30
       0 2961.55    14.7 2950.52    24.5 2944.77    32.5 2941.29    40.6 2936.66
    56.6 2932.69    68.7 2931.86      74 2932.76    80.7 2934.23    84.7 2934.42
    92.7  2932.2    96.8 2932.78   104.8 2935.61   112.8 2935.64   128.9 2937.38
   138.4 2940.17   155.7 2942.18     161  2941.4   173.1 2941.16   192.9 2939.41
   204.3 2939.92   219.5 2937.74   230.1 2935.03   240.8 2935.05   246.1 2936.47
   251.4 2939.34   256.7 2941.14     261 2943.31   277.9  2955.9   286.5 2961.15
#Mann= 3 ,-1,0
       0      .1       0    56.6    .045       0      74      .1       0
#XS Ineff= 2 , 0
                             220            2950
Permanent Ineff=
       F       F
Bank Sta=56.6,74
XS Rating Curve= 0 ,0
Exp/Cntr(USF)=0,0
Exp/Cntr=0.3,0.1

Type RM Length L Ch R = 1 ,368     ,203.7,203.7,203.7
XS GIS Cut Line= 2
2188704.89857172514162.1899552432188812.28826045514374.562275671
#Sta/Elev= 30
       0 2958.67     3.3  2958.3     7.8  2956.4    25.5 2940.47    31.5 2935.81
    37.4 2929.95    43.7 2923.03    48.2 2920.93    52.3 2920.12    57.1 2919.57
    70.6 2918.98    79.5 2919.74    88.5 2919.72      94 2920.12    97.5 2920.79
   106.4 2924.36   133.3 2927.92   141.6 2928.27   146.8 2927.69   168.4 2927.22
   178.2 2929.42   191.6 2931.23   196.1 2931.58   201.1 2930.34   205.1 2930.51
     214 2934.69   218.5 2935.66   227.9 2936.76   236.4 2938.51     238 2938.31
#Mann= 3 ,-1,0
       0      .1       0    52.3    .045       0      94      .1       0
Bank Sta=52.3,94
XS Rating Curve= 0 ,0
Exp/Cntr(USF)=0,0
Exp/Cntr=0.3,0.1

Type RM Length L Ch R = 1 ,164     ,94,94,94
XS GIS Cut Line= 4
2188550.37090231514256.3178784992188570.80242242514336.873607261
2188609.19026015514381.6985503652188680.68754923514378.134847255
#Sta/Elev= 30
       0 2946.14     5.5 2942.61     9.1  2939.6    17.4 2933.43    25.6 2928.37
    29.8 2926.88    33.9 2926.06      38 2924.25    54.5  2918.3    58.7 2917.25
    66.9 2914.01    79.3 2911.71    83.5 2909.68    88.8 2908.82    92.8 2908.57
    99.82906.542   104.6 2905.26   112.7 2904.61   118.3 2904.89  125.49 2906.48
     141 2910.83   145.5 2910.71   153.1 2911.65   161.1 2911.21   165.1 2911.54
   168.4 2912.03   177.2  2914.1   185.2 2914.66   197.2 2917.62   213.7 2920.25
#Mann= 3 ,0,0
       0      .1       0    99.8    .045       0  125.49      .1       0
Bank Sta=99.8,125.49
XS Rating Curve= 0 ,0
Exp/Cntr(USF)=0,0
Exp/Cntr=0.3,0.1

Type RM Length L Ch R = 1 ,70      ,,,
XS GIS Cut Line= 4
2188461.15652525514285.2010027192188468.61862955514379.809825029
2188529.91448625514418.9858725772188685.81916527514381.142343653
#Sta/Elev= 30
       0 2936.51       4 2933.65      12  2930.1      16  2927.9      40 2911.32
    44.1 2907.45    48.1 2905.06    72.2  2905.5    94.9 2904.48   108.6 2905.56
   113.4 2904.94   121.6 2901.11   127.6  2900.3   127.72900.296   146.6 2899.49
   165.1 2899.65     171  2900.3   178.2 2901.29   198.8 2902.84   215.3 2906.87
   227.3 2908.09   237.3  2908.4   264.6 2911.29     277 2912.03   285.2 2914.96
   293.5 2914.32   297.6 2914.67   305.8 2917.14   316.8 2918.55   328.1 2921.26
#Mann= 3 ,-1,0
       0      .1       0   127.6    .045       0     171      .1       0
Bank Sta=127.7,171
XS Rating Curve= 0 ,0
Exp/Cntr(USF)=0,0
Exp/Cntr=0.3,0.1
LCMann Table=0

Chan Stop Cuts=-1
Use User Specified Reach Order=0
Composite Channel Slope=5